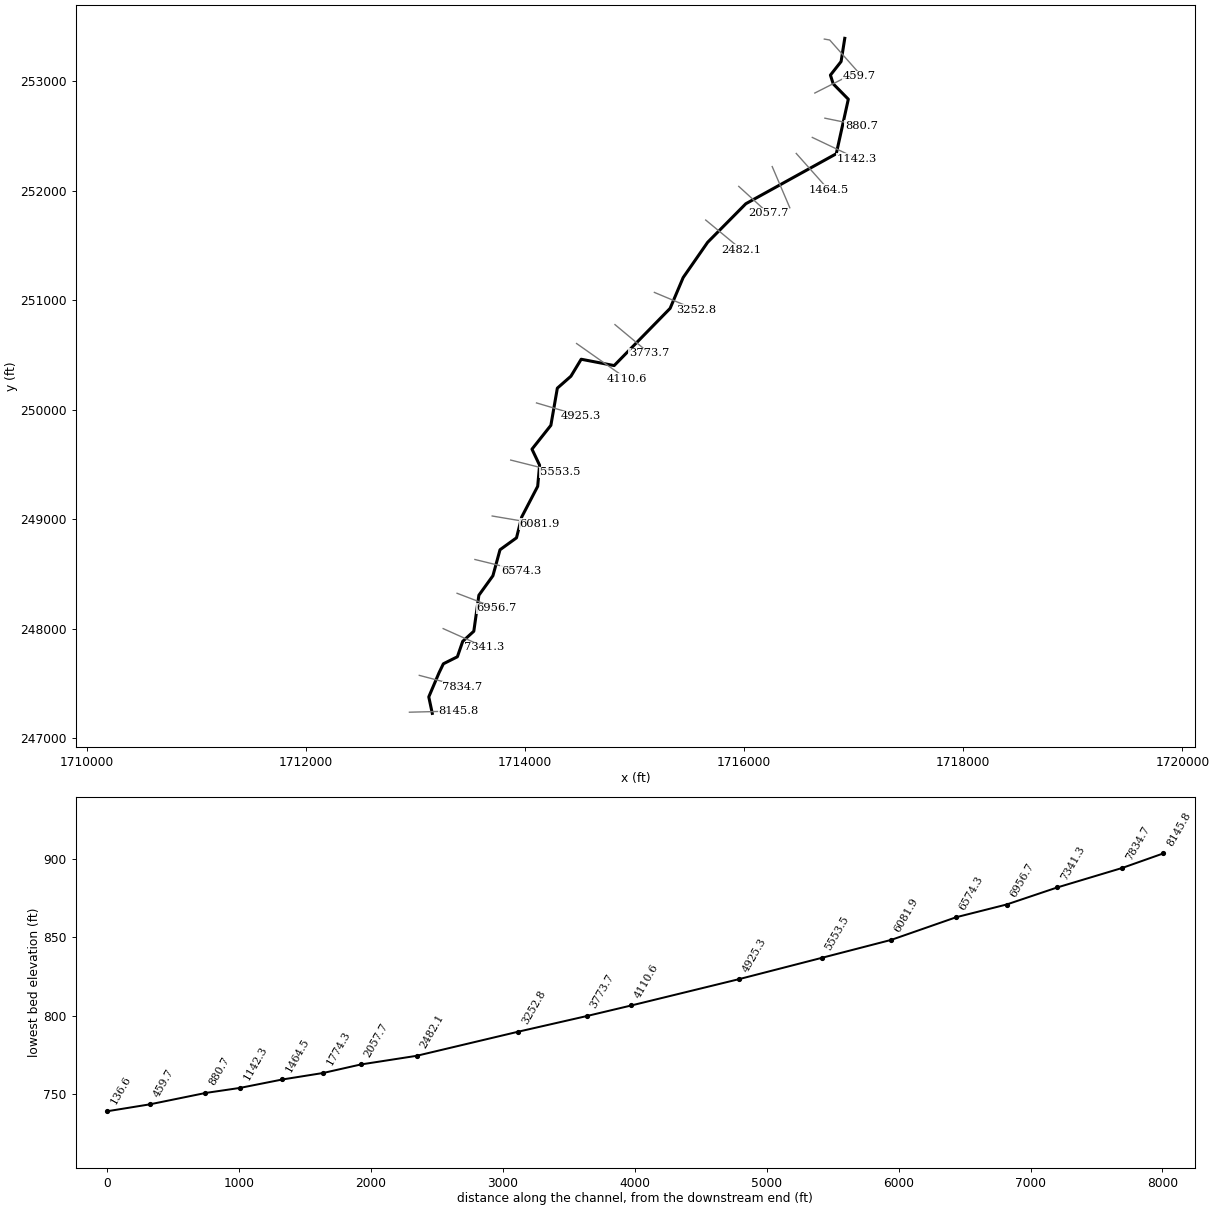
--- SANDLCKCRK.prj (project) ---

Proj Title=SANDLCKCRK
Current Plan=p01
Default Exp/Contr=0,0
English Units
Geom File=g01
Flow File=f01
Plan File=p01
BEGIN DESCRIPTION:
END DESCRIPTION:
DSS Export Rating Curves= 0
DSS Export Rating Curve Sorted= 0
DSS Export Volume Flow Curves= 0
DXF OffsetX= 0
DXF OffsetY= 0
DXF ScaleX= 0
DXF ScaleY= 0

--- SANDLCKCRK.p01 (plan) ---

Plan Title=Floodplain
Program Version=4.00
Geom File=g01
Flow File=f01
K Sum by GR=0
Std Step Tol=0.01
Critical Tol=0.01
Num of Std Step Trials=20
Max Error Tol=0.3
Flow Tol Ratio=0.001
Split Flow NTrial=30
Split Flow Tol=0.02
Split Flow Ratio=0.02
Log Output Level=0
Friction Slope Method=1
Unsteady Friction Slope Method=2
Unsteady Bridges Friction Slope Method=1
Global Log Level=0
CheckData=False
Run HTab=0
Run UNet=0
Run PostProcess=0
UNET Theta=0
UNET Theta Warmup=0
UNET ZTol=0
UNET ZSATol=0
UNET MxIter=0
UNET MaxInSteps=0
UNET DtIC=0
UNET DtMin=0
UNET MaxCRTS=0
UNET WFStab=0
UNET SFStab=0
UNET WFX=0
UNET SFX=0
UNET DSS MLevel=0
UNET DZMax Abort=0
UNET Convert EG Bridges=0
UNET Use Existing IB Tables=0
UNET Froude Limit=0
UNET Froude Power=0
Write IC File=0
Echo Input=False
Echo Output=False
Write Detailed=0

--- SANDLCKCRK.f01 (steady flow) ---

Flow Title=NFF Regression Equation
Program Version=4.00
Number of Profiles=1
Profile Names=P100yr
River Rch & RM=SANDLCKCRK,Main      ,8145.8
924.2843
River Rch & RM=SANDLCKCRK,Main      ,5553.5
950.5514
River Rch & RM=SANDLCKCRK,Main      ,136.6
1398.717
Boundary for River Rch & Prof#=SANDLCKCRK,Main      ,1
Up Type=0
Dn Type=3
Dn Slope=0.014307

--- SANDLCKCRK.g01 (geometry) ---

Geom Title=USGS 10m DEM
Program Version=4.10

River Reach=SANDLCKCRK      ,Main
Reach XY= 30
     1713151.366      247227.806     1713119.369      247378.242
     1713213.046      247598.403      1713252.49      247680.489
     1713380.628      247744.714     1713429.334      247885.665
     1713530.619      247977.824      1713576.81      248306.564
     1713704.987      248484.456     1713769.846      248721.888
     1713920.413      248830.759     1713967.899      249020.704
     1714113.832      249300.989     1714131.205      249494.409
     1714061.713      249640.343     1714234.286      249858.085
     1714293.354      250197.439     1714417.282       250306.31
     1714511.096      250461.509     1714812.229      250403.599
     1715322.996      250925.948     1715442.291      251207.392
     1715665.824      251529.372     1716014.444      251881.466
     1716840.243      252337.798     1716950.272      252835.825
     1716812.446      252975.968     1716786.965      253055.884
     1716884.254      253179.812     1716917.842      253391.763

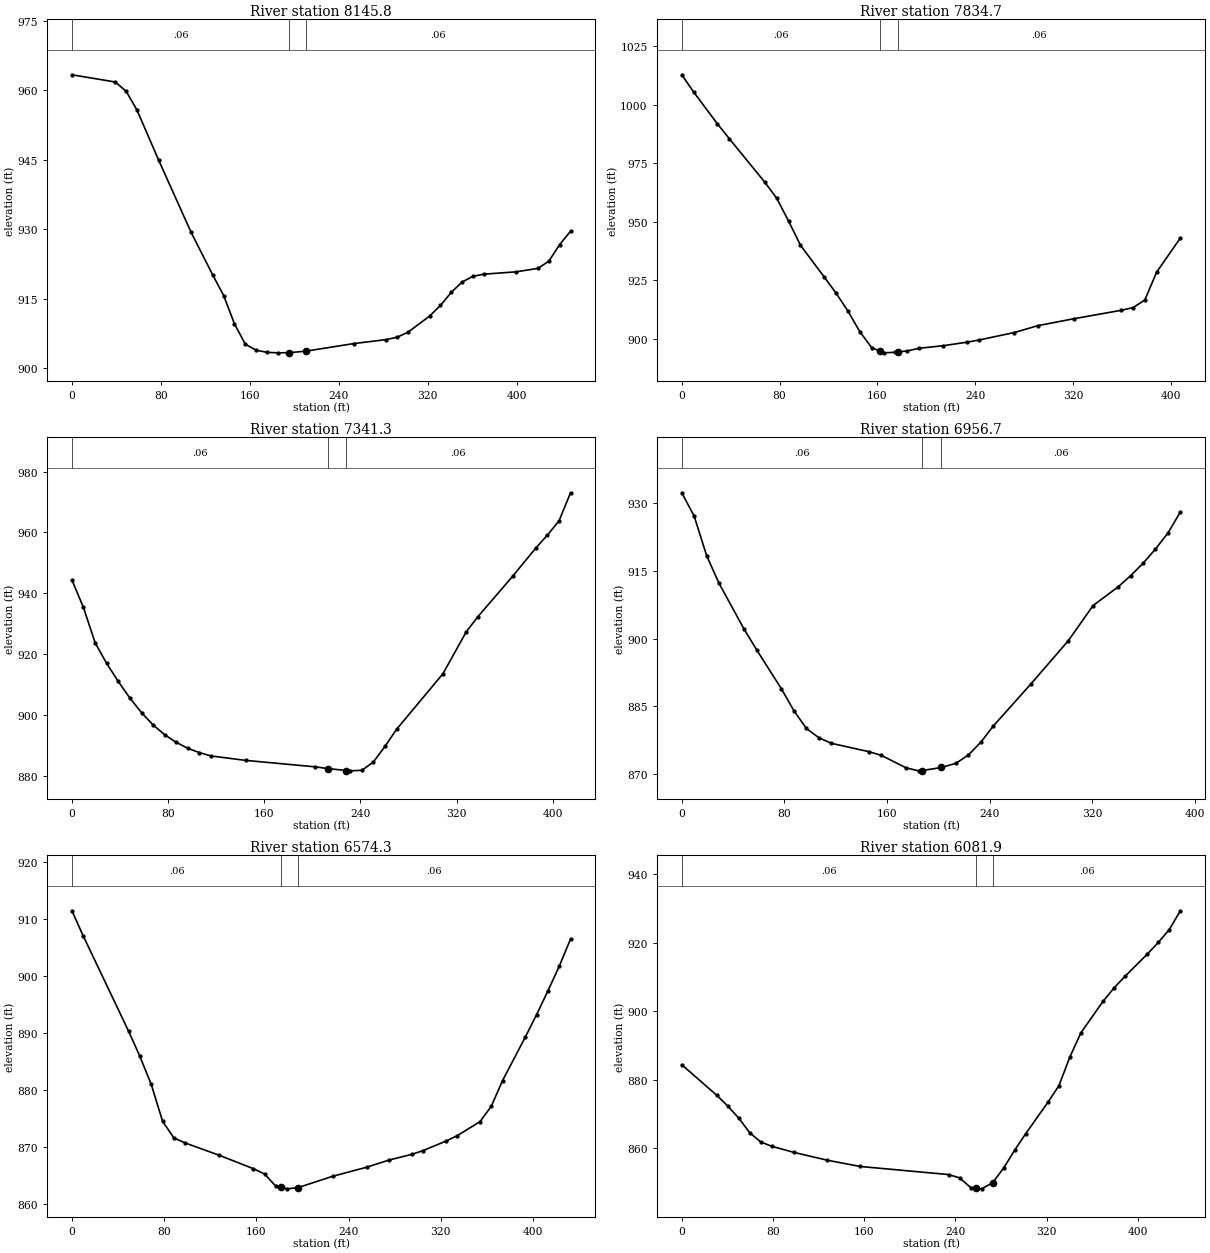
Type RM Length L Ch R = 1 ,8145.8  ,317.5,311.1,304.7
XS GIS Cut Line= 2
     1712942.529      247238.466     1713390.849      247250.177
#Sta/Elev= 30
       0  963.38      39  961.82    48.8  959.81    58.5  955.77      78  944.94
   107.2  929.34   126.7   920.1   136.5  915.67   146.2  909.56     156  905.16
   165.7  903.86   175.5   903.4   185.2  903.29   195.7  903.33   210.7  903.66
   253.5  905.29   282.7  906.15   292.5  906.66   302.2  907.73   321.7  911.23
   331.5  913.53   341.2  916.35     351   918.6   360.7  919.82   370.5  920.29
   399.7   920.8   419.2  921.54     429   923.1   438.7  926.68   448.5  929.57
#Mann= 3 , 0 , 0
       0     .06       0   195.7    .045       0   210.7     .06       0
Bank Sta=195.7,210.7
XS Rating Curve= 0 ,0
Exp/Cntr=0.3,0.1

Type RM Length L Ch R = 1 ,7834.7  ,496.6,492.9,489.1
XS GIS Cut Line= 2
     1713032.649      247574.988     1713427.119      247471.051
#Sta/Elev= 30
       0 1012.78     9.7 1005.45    29.1  991.86    38.8  985.55      68  966.87
    77.7  960.01    87.4  950.29    97.1  939.99   116.6  926.38   126.3  919.49
     136  911.82   145.7  903.04   155.4  896.24   161.8  894.79   165.1  894.04
   174.8  894.29   176.8  894.41   184.5  894.86   194.2  895.99   213.7  897.07
   233.1  898.57   242.8  899.48     272  902.71   291.4  905.66   320.5  908.58
   359.4   912.2   369.1  913.34   378.8  916.58   388.5  928.53   407.9  943.08
#Mann= 3 , 0 , 0
       0     .06       0   161.8    .045       0   176.8     .06       0
Bank Sta=161.8,176.8
XS Rating Curve= 0 ,0
Exp/Cntr=0.3,0.1

Type RM Length L Ch R = 1 ,7341.3  ,383.4,384.6,385.7
XS GIS Cut Line= 2
     1713250.766      248001.837     1713629.323      247832.201
#Sta/Elev= 30
       0  944.38     9.6  935.32    19.3  923.74    28.9  916.94    38.6  910.99
    48.2  905.56    57.9  900.74    67.5  896.72    77.2  893.47    86.8  890.97
    96.5     889   106.1   887.6   115.8   886.5   144.7  885.04   202.6  882.92
   213.1  882.34   228.1  881.72   231.5  881.61   241.2  881.78   250.8  884.52
   260.5  889.68   270.1  895.28   308.7  913.56     328   927.3   337.6  932.24
   366.6  945.57   385.9  954.86   395.5   959.1   405.2  963.78   414.8  973.04
#Mann= 3 , 0 , 0
       0     .06       0   213.1    .045       0   228.1     .06       0
Bank Sta=213.1,228.1
XS Rating Curve= 0 ,0
Exp/Cntr=0.3,0.1

Type RM Length L Ch R = 1 ,6956.7  ,379.1,382,384.9
XS GIS Cut Line= 2
     1713377.775      248324.421     1713740.641      248185.544
#Sta/Elev= 30
       0  932.29     9.7   927.1    19.4  918.35    29.1  912.21    48.6  902.08
    58.3  897.54    77.7  888.86    87.4  884.03    97.1  880.12   106.8  878.06
   116.6  876.82   145.7  874.98   155.4  874.17   174.8  871.39   184.6  870.73
   187.3   870.8   202.3  871.47   213.7  872.41   223.4  874.25   233.1  877.11
   242.8  880.67     272  889.96   301.1  899.51   320.5  907.33     340  911.46
   349.7  913.92   359.4  916.68   369.1  919.84   378.8  923.37   388.5  928.05
#Mann= 3 , 0 , 0
       0     .06       0   187.3    .045       0   202.3     .06       0
Bank Sta=187.3,202.3
XS Rating Curve= 0 ,0
Exp/Cntr=0.3,0.1

Type RM Length L Ch R = 1 ,6574.3  ,490.6,492.3,494
XS GIS Cut Line= 2
     1713540.625       248632.89     1713960.923      248530.434
#Sta/Elev= 30
       0  911.49     9.8  907.08    49.2  890.32      59   885.9    68.8  880.99
    78.7  874.48    88.5  871.57    98.3  870.69   127.8  868.53   157.3  866.18
   167.1  865.25     177  863.07   181.3  862.88   186.8  862.63   196.3  862.85
   226.1  864.83   255.6  866.42   275.3   867.7     295  868.69   304.8  869.36
   324.4  871.01   334.3  871.97     354  874.43   363.8  877.12   373.6  881.64
   393.3  889.27   403.1  893.22   412.9  897.38   422.8  901.74   432.6  906.52
#Mann= 3 , 0 , 0
       0     .06       0   181.3    .045       0   196.3     .06       0
Bank Sta=181.3,196.3
XS Rating Curve= 0 ,0
Exp/Cntr=0.3,0.1

Type RM Length L Ch R = 1 ,6081.9  ,530.3,528.3,526.3
XS GIS Cut Line= 3
     1713698.473      249030.049     1713709.586      249028.176
     1714129.559      248957.398
#Sta/Elev= 30
       0  884.45    30.6  875.55    40.3   872.4      50  868.84    59.7  864.54
    69.4  861.85      79  860.62    98.4  858.84   127.4  856.57   156.5  854.73
   233.9  852.37   243.6   851.4   253.3  848.58   257.6  848.41   262.9   848.2
   272.6  849.99   282.3  854.31     292  859.53   301.6  864.32     321  873.46
   330.7  878.33   340.4  886.79     350  893.78   369.4  902.96   379.1   906.9
   388.8  910.31   408.1  916.72   417.8  920.14   427.5  923.93   437.2   929.4
#Mann= 3 , 0 , 0
       0     .06       0   257.6    .045       0   272.6     .06       0
Bank Sta=257.6,272.6
XS Rating Curve= 0 ,0
Exp/Cntr=0.3,0.1

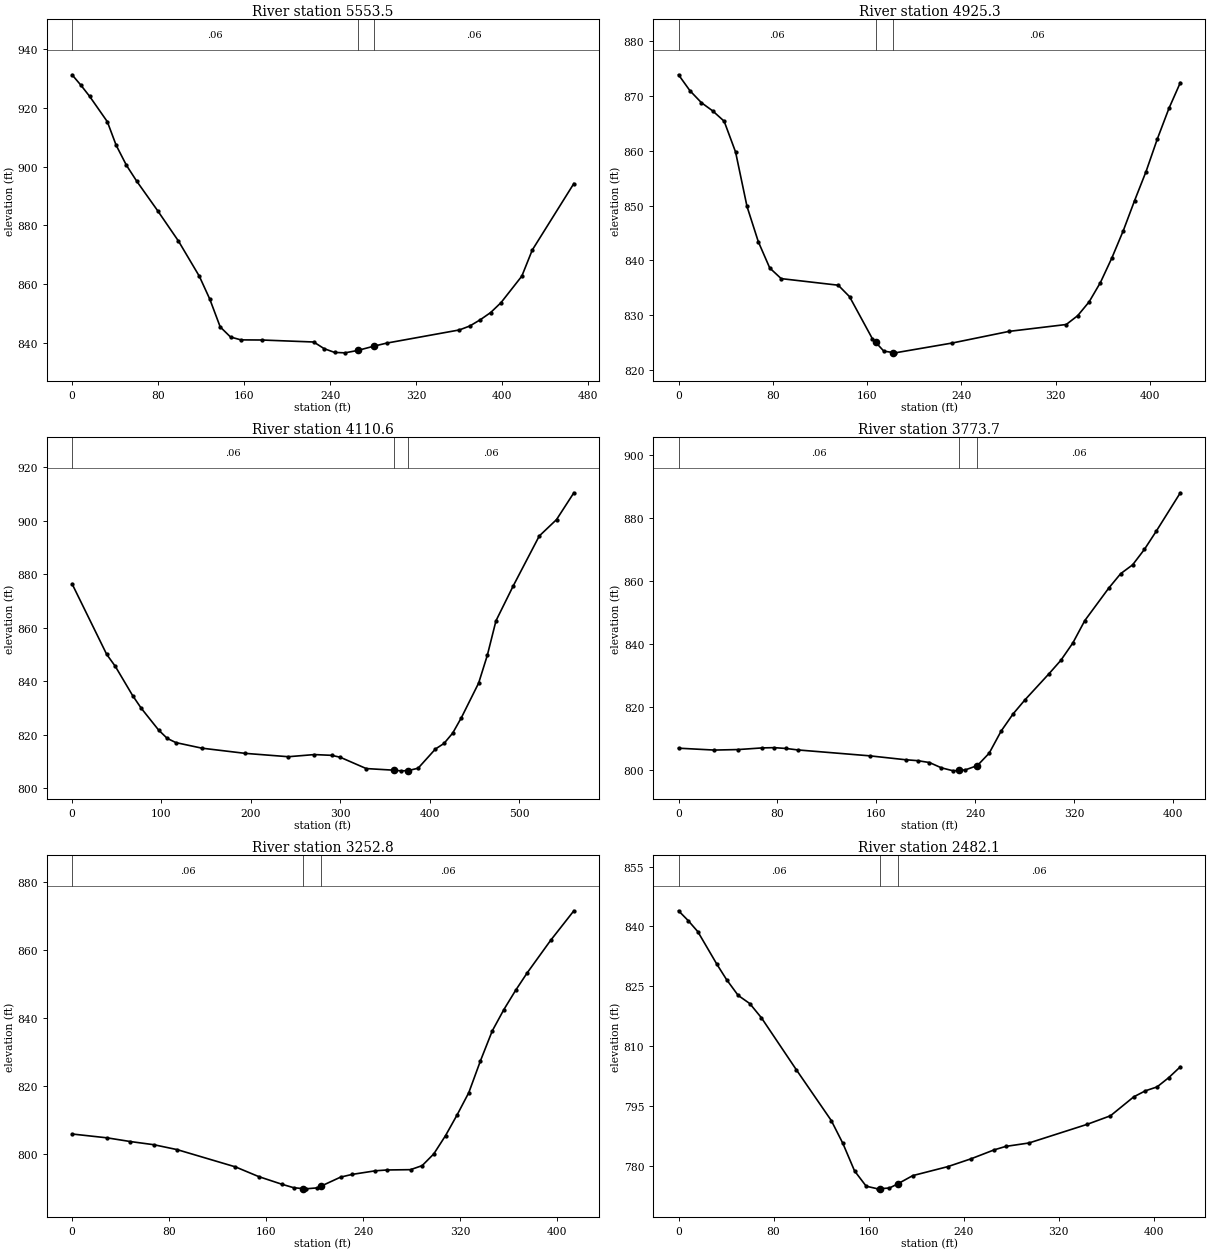
Type RM Length L Ch R = 1 ,5553.5  ,629.2,628.1,627
XS GIS Cut Line= 3
      1713867.51      249540.881     1713907.253      249530.917
     1714320.295      249427.365
#Sta/Elev= 30
       0  931.18     8.2  927.65    16.4  923.82    32.8  915.24      41  907.25
    50.6  900.42    60.3  894.95    79.7  884.96      99  874.68   118.4  862.73
   128.1  854.98   137.8  845.53   147.4   842.1   157.1  841.12   176.5  841.08
   224.8   840.4   234.5  838.14   244.2  836.86   253.9  836.72   265.7  837.53
   280.7  838.98   292.6  840.02   360.3   844.5     370  845.84   379.7  847.95
   389.4  850.41     399  853.76   418.4  862.78   428.1  871.64   466.8  894.24
#Mann= 3 , 0 , 0
       0     .06       0   265.7    .045       0   280.7     .06       0
Bank Sta=265.7,280.7
XS Rating Curve= 0 ,0
Exp/Cntr=0.3,0.1

Type RM Length L Ch R = 1 ,4925.3  ,775.4,814.4,813.7
XS GIS Cut Line= 2
     1714103.071      250062.589     1714511.371      249941.919
#Sta/Elev= 30
       0  873.87     9.7  870.96    19.4  868.78      29  867.28    38.7   865.4
    48.4  859.78    58.1  849.85    67.7  843.41    77.4  838.62    87.1  836.68
   135.5  835.48   145.1  833.39   164.5  825.71   167.2  825.08   174.2  823.45
   182.2  823.19   183.8  823.14   232.2  824.93   280.6  827.06     329  828.31
   338.7  829.92   348.4  832.44     358  835.97   367.7  840.45   377.4  845.43
     387  850.92   396.7  856.21   406.4  862.23   416.1  867.72   425.8  872.44
#Mann= 3 , 0 , 0
       0     .06       0   167.2    .045       0   182.2     .06       0
Bank Sta=167.2,182.2
XS Rating Curve= 0 ,0
Exp/Cntr=0.3,0.1

Type RM Length L Ch R = 1 ,4110.6  ,384.8,336.8,328.4
XS GIS Cut Line= 2
     1714468.894      250605.103     1714927.854      250282.211
#Sta/Elev= 30
       0  876.34    38.7  849.98    48.4  845.47    67.7  834.58    77.4  829.81
    96.8  821.67   106.4  818.56   116.1  816.98   145.1   814.9   193.5  812.96
   241.9   811.7   270.9   812.5   290.3  812.22   299.9   811.5     329  807.27
   360.5  806.65   367.7  806.42   375.5  806.48     387   807.4   406.4  814.59
     416  816.67   425.7  820.54   435.4   826.3   454.7  839.23   464.4   849.6
   474.1  862.53   493.4  875.58   522.5  894.23   541.8  900.36   561.2  910.39
#Mann= 3 , 0 , 0
       0     .06       0   360.5    .045       0   375.5     .06       0
Bank Sta=360.5,375.5
XS Rating Curve= 0 ,0
Exp/Cntr=0.3,0.1

Type RM Length L Ch R = 1 ,3773.7  ,513.9,520.7,527.4
XS GIS Cut Line= 2
      1714819.46      250777.741     1715131.341      250517.592
#Sta/Elev= 30
       0  806.89      29  806.29    48.4  806.46    67.7  806.98    77.4  807.06
      87   806.8    96.7  806.33   154.7  804.46   183.7  803.22   193.4  802.93
   203.1  802.33   212.7  800.65   222.4  799.69   226.8  799.83   232.1     800
   241.8  801.35   251.4   805.3   261.1  812.34   270.8  817.81   280.4  822.27
   299.8  830.55   309.4  834.82   319.1  840.33   328.8  847.46   348.1  857.74
   357.8  862.36   367.5  865.18   377.1  870.12   386.8  875.98   406.1  888.08
#Mann= 3 , 0 , 0
       0     .06       0   226.8    .045       0   241.8     .06       0
Bank Sta=226.8,241.8
XS Rating Curve= 0 ,0
Exp/Cntr=0.3,0.1

Type RM Length L Ch R = 1 ,3252.8  ,777,770.6,764
XS GIS Cut Line= 2
     1715179.482      251071.744     1715561.172      250911.861
#Sta/Elev= 30
       0  805.83    28.9   804.7    48.1  803.61    67.4  802.68    86.6  801.24
   134.7  796.16     154  793.29   173.2  791.03   182.8  790.03   190.6  789.76
   192.5   789.7   202.1  789.98   205.6  790.54   221.4  793.14     231  793.95
   250.2  795.01   259.8  795.25   279.1  795.34   288.7  796.53   298.3  799.98
     308  805.37   317.6   811.5   327.2  818.03   336.8  827.39   346.5  836.15
   356.1  842.44   365.7  848.05   375.3  853.22   394.6  862.77   413.8  871.49
#Mann= 3 , 0 , 0
       0     .06       0   190.6    .045       0   205.6     .06       0
Bank Sta=190.6,205.6
XS Rating Curve= 0 ,0
Exp/Cntr=0.3,0.1

Type RM Length L Ch R = 1 ,2482.1  ,425.5,424.3,423.2
XS GIS Cut Line= 3
     1715648.076      251732.612     1715679.254      251706.848
     1715973.749       251463.49
#Sta/Elev= 30
       0  843.93     8.1  841.48    16.2  838.72    32.4  830.49    40.4  826.72
    50.2  822.75      60   820.7    69.8  817.14    99.2  804.13   128.6  791.43
   138.4  785.68   148.2  778.82     158  774.99   167.8  774.33   169.4  774.36
   177.6  774.54   184.4  775.55   197.2  777.64   226.6  779.88   246.2  781.84
   265.8  784.09   275.5  784.95   295.1  785.81   344.1  790.48   363.7  792.62
   383.3  797.36   393.1  798.87   402.9  799.84   412.7  802.15   422.5  804.88
#Mann= 3 , 0 , 0
       0     .06       0   169.4    .045       0   184.4     .06       0
Bank Sta=169.4,184.4
XS Rating Curve= 0 ,0
Exp/Cntr=0.3,0.1

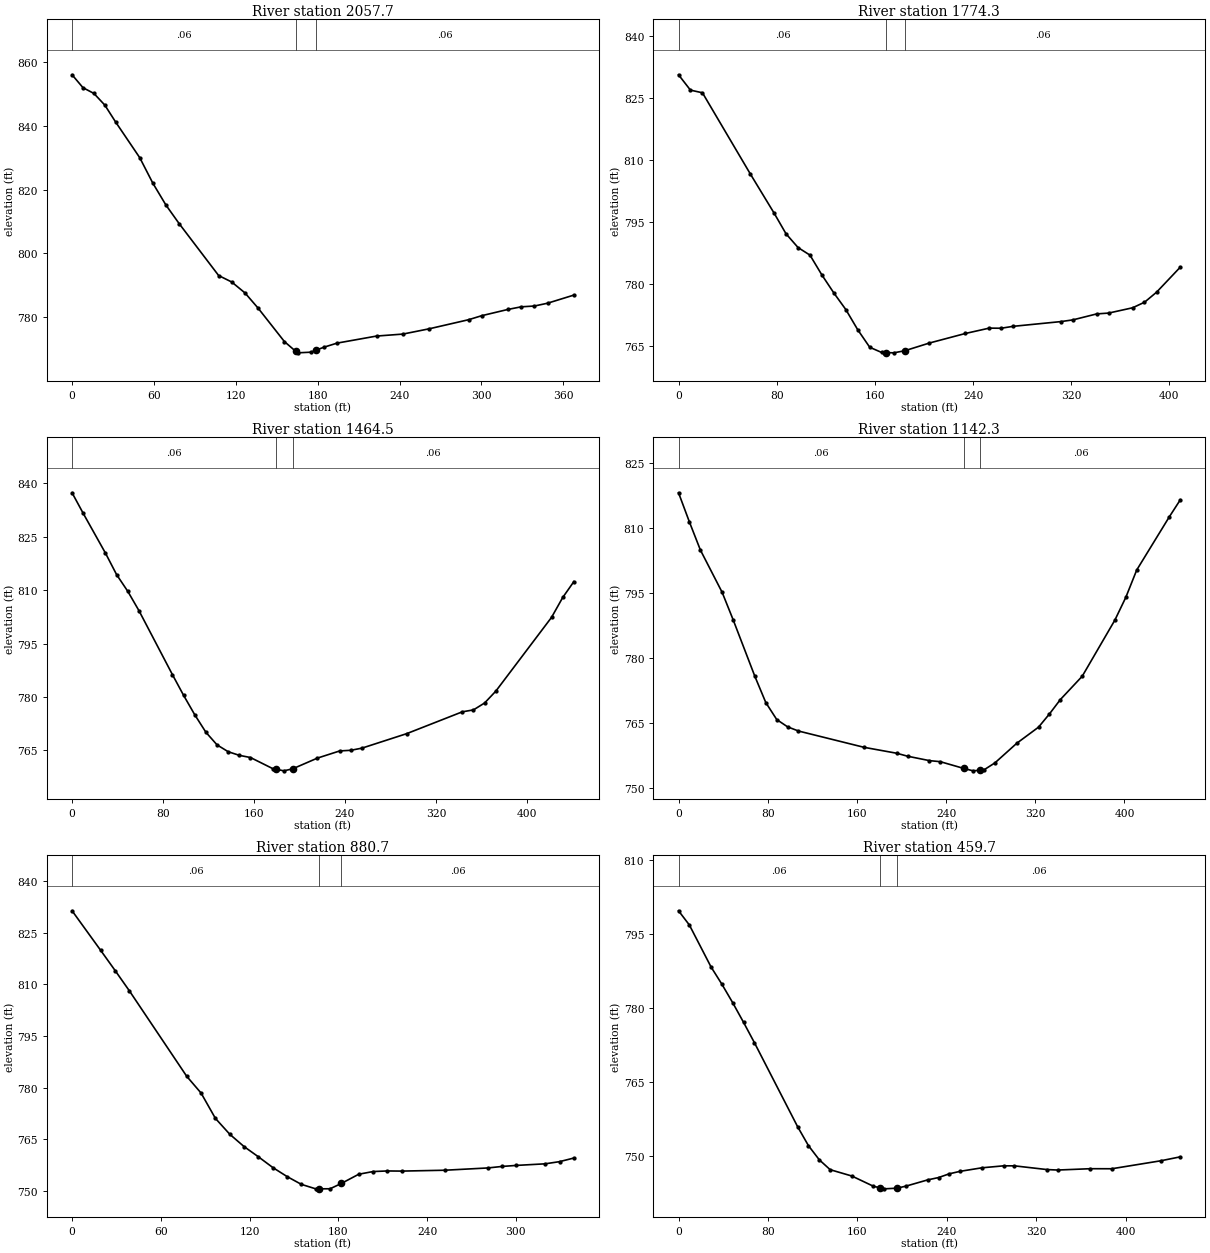
Type RM Length L Ch R = 1 ,2057.7  ,293.2,283.5,273.7
XS GIS Cut Line= 3
     1715949.727      252039.956     1715979.244      252013.066
     1716221.539      251792.335
#Sta/Elev= 30
       0  855.99       8  851.94      16  850.14      24  846.48    31.9  841.19
    49.6  829.99    59.2  821.99    68.8  815.13    78.5   809.3   107.4  793.04
     117  791.01   126.7  787.59   136.3  782.83   155.6  772.33     164  769.24
   165.2   768.8   174.9     769     179  769.67   184.5  770.56   194.2  771.85
   223.1  774.06   242.4  774.68   261.6  776.33   290.6  779.19   300.2  780.45
   319.5  782.42   329.1  783.23   338.8  783.48   348.4  784.36   367.7  786.91
#Mann= 3 , 0 , 0
       0     .06       0     164    .045       0     179     .06       0
Bank Sta=164,179
XS Rating Curve= 0 ,0
Exp/Cntr=0.3,0.1

Type RM Length L Ch R = 1 ,1774.3  ,301.9,309.5,317.2
XS GIS Cut Line= 2
     1716255.405      252220.641     1716416.123      251844.602
#Sta/Elev= 30
       0  830.68     9.7  826.97    19.5  826.32    58.4  806.74    77.9   797.2
    87.6  792.21    97.4  788.88   107.1  787.05   116.8  782.26   126.6  777.88
   136.3  773.89     146  769.01   155.8  764.76   165.5   763.5   169.3  763.47
   175.3  763.41   184.3  763.91   204.5  765.79   233.7  768.09   253.2  769.39
   262.9  769.36   272.6  769.82   311.6  770.97   321.3  771.38   340.8  772.83
   350.5  773.03     370  774.31   379.7  775.65   389.5  778.07   408.9  784.15
#Mann= 3 , 0 , 0
       0     .06       0   169.3    .045       0   184.3     .06       0
Bank Sta=169.3,184.3
XS Rating Curve= 0 ,0
Exp/Cntr=0.3,0.1

Type RM Length L Ch R = 1 ,1464.5  ,313.6,322.3,331
XS GIS Cut Line= 2
     1716474.869      252340.645     1716768.246      252010.972
#Sta/Elev= 30
       0  837.33     9.8  831.55    29.4  820.37    39.2  814.33      49  809.66
    58.8  804.25    88.3  786.25    98.1  780.45   107.9     775   117.7  770.09
   127.5  766.55   137.3  764.63   147.1  763.61   156.9     763   176.5  759.88
   179.1  759.72   186.3  759.26   194.1  759.84   215.8  762.84   235.4  764.85
   245.2  765.03     255  765.64   294.2  769.69   343.2  775.83     353  776.37
   362.8  778.31   372.7  781.65   421.7  802.36   431.5  807.93   441.3  812.39
#Mann= 3 , 0 , 0
       0     .06       0   179.1    .045       0   194.1     .06       0
Bank Sta=179.1,194.1
XS Rating Curve= 0 ,0
Exp/Cntr=0.3,0.1

Type RM Length L Ch R = 1 ,1142.3  ,256.1,261.6,267.1
XS GIS Cut Line= 2
     1716621.476      252486.888     1717028.024      252293.672
#Sta/Elev= 30
       0   818.2     9.8  811.42    19.6  804.96    39.1  795.18    48.9  788.88
    68.5  775.72    78.3  769.66    88.1  765.74    97.8  764.06   107.6  763.09
   166.4  759.32   195.7  757.95   205.5  757.26   225.1  756.24   234.8     756
   255.8  754.44   264.2  753.88   270.8  754.03     274  754.11   283.8  755.72
   303.4  760.26   322.9  763.98   332.7  767.04   342.5  770.37   362.1  775.76
   391.4  788.75   401.2  794.01     411  800.34   440.3  812.67   450.1  816.58
#Mann= 3 , 0 , 0
       0     .06       0   255.8    .045       0   270.8     .06       0
Bank Sta=255.8,270.8
XS Rating Curve= 0 ,0
Exp/Cntr=0.3,0.1

Type RM Length L Ch R = 1 ,880.7   ,405.7,420.8,435.2
XS GIS Cut Line= 2
     1716736.291      252662.687     1717068.598      252594.849
#Sta/Elev= 28
       0  831.34    19.4  819.82    29.1     814    38.8  808.07    77.5  783.31
    87.2  778.45    96.9  771.09   106.6  766.49   116.3   762.9     126  759.93
   135.7  756.83   145.4   754.2     155  751.95   164.7  750.65     167  750.65
   174.4  750.67     182  752.21   193.8  754.89   203.5  755.67   213.2  755.84
   222.9   755.8     252  756.05     281  756.71   290.7  757.15   300.4  757.45
   319.8  757.91   329.5  758.54   339.2  759.59
#Mann= 3 , 0 , 0
       0     .06       0     167    .045       0     182     .06       0
Bank Sta=167,182
XS Rating Curve= 0 ,0
Exp/Cntr=0.3,0.1

Type RM Length L Ch R = 1 ,459.7   ,354.7,323.2,288.4
XS GIS Cut Line= 3
     1716644.258      252892.238     1716989.828      253067.409
     1717046.933      253045.194
#Sta/Elev= 30
       0  799.64     9.7  796.76    29.1  788.27    38.7  784.82    48.4  781.07
    58.1   777.1    67.8     773   106.5  755.98   116.2  752.15   125.9  749.29
   135.6   747.3     155  746.02   174.3  743.95   180.3  743.63     184  743.43
   195.3  743.56   203.4  743.98   222.8  745.24   232.5  745.71   242.1  746.47
   251.8  746.97   271.2  747.68   290.6  748.08   300.3  748.08   329.3  747.33
     339  747.23   368.1   747.5   387.4  747.49   431.2   749.1   448.7   749.9
#Mann= 3 , 0 , 0
       0     .06       0   180.3    .045       0   195.3     .06       0
Bank Sta=180.3,195.3
XS Rating Curve= 0 ,0
Exp/Cntr=0.3,0.1

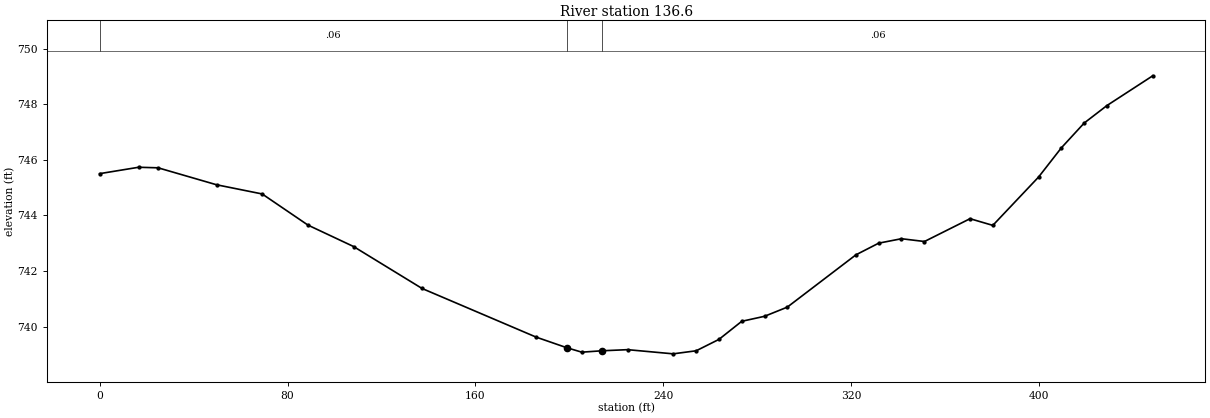
Type RM Length L Ch R = 1 ,136.6   ,121.2,136.4,155.6
XS GIS Cut Line= 3
     1716731.114      253384.964     1716780.227      253376.672
     1717044.614      253078.432
#Sta/Elev= 30
       0   745.5    16.6  745.73    24.9  745.71    49.8   745.1    69.2  744.77
    88.7  743.65   108.1  742.88   137.3  741.37   185.9  739.62   198.9  739.24
   205.3  739.08   213.9  739.13   224.8  739.17   244.2  739.02     254  739.13
   263.7  739.54   273.4  740.19   283.1  740.37   292.8   740.7     322  742.58
   331.7     743   341.4  743.16   351.2  743.06   370.6  743.88   380.3  743.64
   399.8  745.38   409.5  746.43   419.2  747.32   428.9  747.95   448.4  749.02
#Mann= 3 , 0 , 0
       0     .06       0   198.9    .045       0   213.9     .06       0
Bank Sta=198.9,213.9
XS Rating Curve= 0 ,0
Exp/Cntr=0.3,0.1

Chan Stop Cuts=-1
Use User Specified Reach Order=0
Composite Channel Slope=5